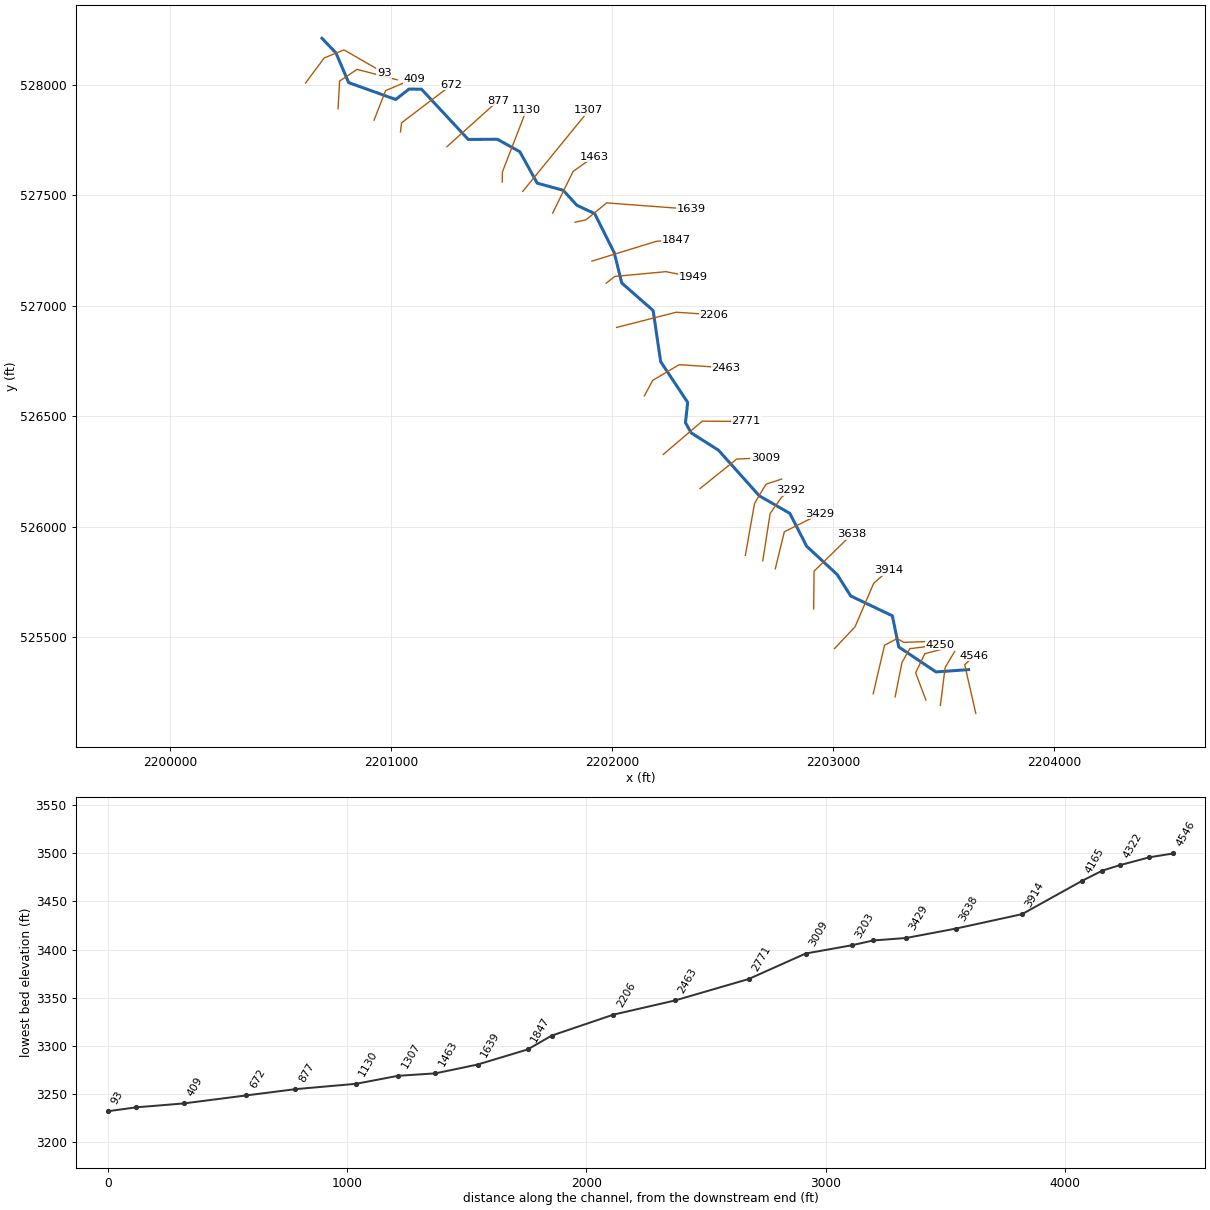
--- RFLTHWCKT1.prj (project) ---

Proj Title=RFLTHWCKT1
Current Plan=p01
Default Exp/Contr=0,0
English Units
Geom File=g01
Flow File=f01
Plan File=p01
BEGIN DESCRIPTION:
----------MODEL BY WOOD PLC 2022----------
AFH study
Randolph County, WV
HEC-RAS Version: RAS 6.2
Vertical Datum: NAVD88
Projection: NAD 1983 StatePlane West Virginia S FIPS 4702 (US Feet)
Terrain: 1-meter LIDAR (FEMA Region III 3DEP collected 2016-2018)
Land Use: 2019 NLCD
Hydrologic Method:
WV SIR2010-5033 regression equations
Additional Model Notes:
None
END DESCRIPTION:
DSS Export Rating Curves= 0
DSS Export Rating Curve Sorted= 0
DSS Export Volume Flow Curves= 0
DXF OffsetX= 0
DXF OffsetY= 0
DXF ScaleX= 0
DXF ScaleY= 0

--- RFLTHWCKT1.p01 (plan) ---

Plan Title=Floodplain
Program Version=6.20
Short Identifier=Floodplain
Geom File=g01
Flow File=f01
Subcritical Flow
K Sum by GR= 0
Std Step Tol= 0.01
Critical Tol= 0.01
Num of Std Step Trials= 20
Max Error Tol= 0.3
Flow Tol Ratio= 0.001
Split Flow NTrial= 30
Split Flow Tol= 0.02
Split Flow Ratio= 0.02
Log Output Level= 0
Friction Slope Method= 1
Unsteady Friction Slope Method= 2
Unsteady Bridges Friction Slope Method= 1
Parabolic Critical Depth
Global Vel Dist= 0 , 0 , 0
Global Log Level= 0
CheckData=True
Encroach Param=-1 ,0,0, 0
Mapping Interval=1HOUR
Computation Time Step Use Courant=        0
Computation Time Step Use Time Series=    0
Computation Time Step Count To Double=0
Computation Time Step Max Doubling=0
Computation Time Step Max Halving=0
Computation Time Step Residence Courant=0
Run HTab= 0
Run UNet= 0
Run Sediment= 0
Run PostProcess= 0
Run WQNet= 0
Run RASMapper=-1
UNET Theta= 0
UNET Theta Warmup= 0
UNET ZTol= 0
UNET ZSATol= 0
UNET MxIter= 0
UNET Max Iter WO Improvement= 0
UNET MaxInSteps= 0
UNET DtIC= 0
UNET DtMin= 0
UNET MaxCRTS= 0
UNET WFStab= 0
UNET SFStab= 0
UNET WFX= 1
UNET SFX= 1
UNET Gravity=32.174
UNET 1D Methodology=Finite Difference
UNET DSS MLevel= 1
UNET Pardiso=0
UNET DZMax Abort= 0
UNET Use Existing IB Tables= 0
UNET Froude Reduction=False
UNET Froude Limit= 0
UNET Froude Power= 0
UNET D1 Cores= 0
UNET WindReference=Eulerian
UNET WindDragFormulation=Hsu (1988)
UNET D2 Coriolis=0
UNET D2 Cores= 0
UNET D2 Theta= 1
UNET D2 Theta Warmup= 1
UNET D2 Z Tol= 0.01
UNET D2 Volume Tol= 0.01
UNET D2 Max Iterations= 20
UNET D2 Equation= 0
UNET D2 RampUpFraction=0.1
UNET D2 TimeSlices= 1
UNET D2 Turbulence Formulation=Non-Conservative (original)
UNET D2 Eddy Viscosity=0.3
UNET D2 Transverse Eddy Viscosity=0.1
UNET D2 Smagorinsky Mixing=0
UNET D2 BCVolumeCheck=0
UNET D2 Cores=0
UNET D2 SolverType=PARDISO (Direct)
UNET D2 Minimum Iterations= 2147483647
UNET D2 Maximum Iterations= 2147483647
UNET D2 Restart Number= 10
UNET D2 Relaxation Coeff=1.3
UNET D2 SOR Precondition Iterations= 10
UNET D2 ILUT Maximum Fill= 8
UNET D2 ILUT Tolerance=1E-08
UNET D1D2 MaxIter= 0
UNET D1D2 ZTol=0.01
UNET D1D2 QTol=0.1
UNET D1D2 MinQTol=1
Write IC File= 0
Write IC File at Fixed DateTime=0
Write IC File at Sim End=0
Echo Input=False
Echo Parameters=False
Echo Output=False
Write Detailed= 0
HDF Write Warmup=0
HDF Write Time Slices=0
HDF Flush=0
HDF Compression= 1
HDF Chunk Size= 1
HDF Spatial Parts= 1
HDF Use Max Rows=0
HDF Fixed Rows= 1
Calibration Method= 0
Calibration Iterations= 20
Calibration Max Change=0.05
Calibration Tolerance=0.2
Calibration Maximum=1.5
Calibration Minimum=0.5
Calibration Optimization Method= 1
WQ AD Non Conservative
WQ ULTIMATE=-1
WQ Max Comp Step=1HOUR
WQ Output Interval=15MIN
WQ Output Selected Increments= 0
WQ Output face flow=0
WQ Output face velocity=0
WQ Output face area=0
WQ Output face dispersion=0
WQ Output cell volume=0
WQ Output cell surface area=0
WQ Output cell continuity=0
WQ Output cumulative cell continuity=0
WQ Output face conc=0
WQ Output face dconc_dx=0
WQ Output face courant=0
WQ Output face peclet=0
WQ Output face adv mass=0
WQ Output face disp mass=0
WQ Output cell mass=0
WQ Output cell source sink temp=0
WQ Output nsm pathways=0
WQ Output nsm derived pathways=0
WQ Create Restart=0
WQ Fixed Restart=0
WQ System Summary=0
WQ Write To DSS=0
Sorting and Armoring Iterations= 10
XS Update Threshold= 0.02
Bed Roughness Predictor= 0
Hydraulics Update Threshold= 0.02
Energy Slope Method= 1
Volume Change Method= 1
Sediment Retention Method= 0
Sediment TS Multiplier= 1
Warm Up Method= 0
XS Weighting Method= 0
Number of US Weighted Cross Sections= 1
Number of DS Weighted Cross Sections= 1
Upstream XS Weight=0
Main XS Weight=1
Downstream XS Weight=0
Number of DS XS's Weighted with US Boundary= 1
Upstream Boundary Weight= 1
Weight of XSs Associated with US Boundary= 0
Number of US XS's Weighted with DS Boundary= 1
Downstream Boundary Weight= 0.5
Weight of XSs Associated with DS Boundary= 0.5
Percentile Method= 0
Sediment Output Level= 3
Mass or Volume Output= 0
Output Increment Type= 1
Profile and TS Output Increment= 1
Transport Output Increment 1
XS Output Flag= 0
XS Output Increment= 10
Read HDF5 Sediment Hotstart= 0
Sediment Hotstart Type= 0
Write Gradation File= 0
Read Gradation Hotstart= 0
Write HDF5 File= 1
Write Binary Output= 1
Write DSS Sediment File= 0
DSS Sediment Output Type= 1
SV Curve= 0
Specific Gage Flag= 0
Subcell Erosion Methods= 0
Subcell Deposition Methods= 0
Advection Scheme= 1
Matrix Solver= 0
Implicit Weighting Factor= 1
Maximum Outer Loop Convergence Iterations= 5
Convergence Maximum Absolute= 0.001
Convergence RMSE= 0.0001
Grain Fractions Max Abs Error= 0.001
Max Subgrid Regions= 1
Max Subgrid Length Scale= 3.402823E+38
Initial Layer Thickness= 3.402823E+38
Min Layer Thickness= 3.402823E+38
Max Layer Thickness= 3.402823E+38
Number of Layers= 5

--- RFLTHWCKT1.f01 (steady flow) ---

Flow Title=Flow
Program Version=6.20
Number of Profiles= 1
Profile Names=P100yr
River Rch & RM=RFLTHWCKT1,Main,4546
     368
River Rch & RM=RFLTHWCKT1,Main,1949
     411
Boundary for River Rch & Prof#=RFLTHWCKT1,Main            , 1
Up Type= 0
Dn Type= 3
Dn Slope=0.02043
DSS Import GetInterval= 0
DSS Import GetPeak= 0
DSS Import FillOption= 0

--- RFLTHWCKT1.g01 (geometry) ---

Geom Title=Geometry
Program Version=6.20

River Reach=RFLTHWCKT1      ,Main
Reach XY= 30
     2203614.367      525352.755     2203466.797      525342.338
     2203298.394      525455.186     2203269.315      525596.245
     2203080.986      525686.067     2203019.315      525783.311
     2202881.728      525910.915     2202805.339      526059.787
     2202667.318      526139.214     2202482.422      526345.811
     2202359.159      526423.936     2202333.117      526470.377
     2202343.099      526561.957     2202220.704      526746.852
     2202186.849      526977.755     2202044.922      527102.321
2202010.75956283527239.726164253     2201922.527      527416.123
     2201841.363      527454.318     2201779.732      527522.026
      2201662.11      527554.144     2201583.562      527696.376
     2201481.988      527752.929     2201350.044      527752.061
     2201138.476      527979.402     2201082.103      527980.038
2201021.65792947527932.9439919332200808.87276793528009.161222324
     2200751.322      528143.545     2200688.356      528209.615

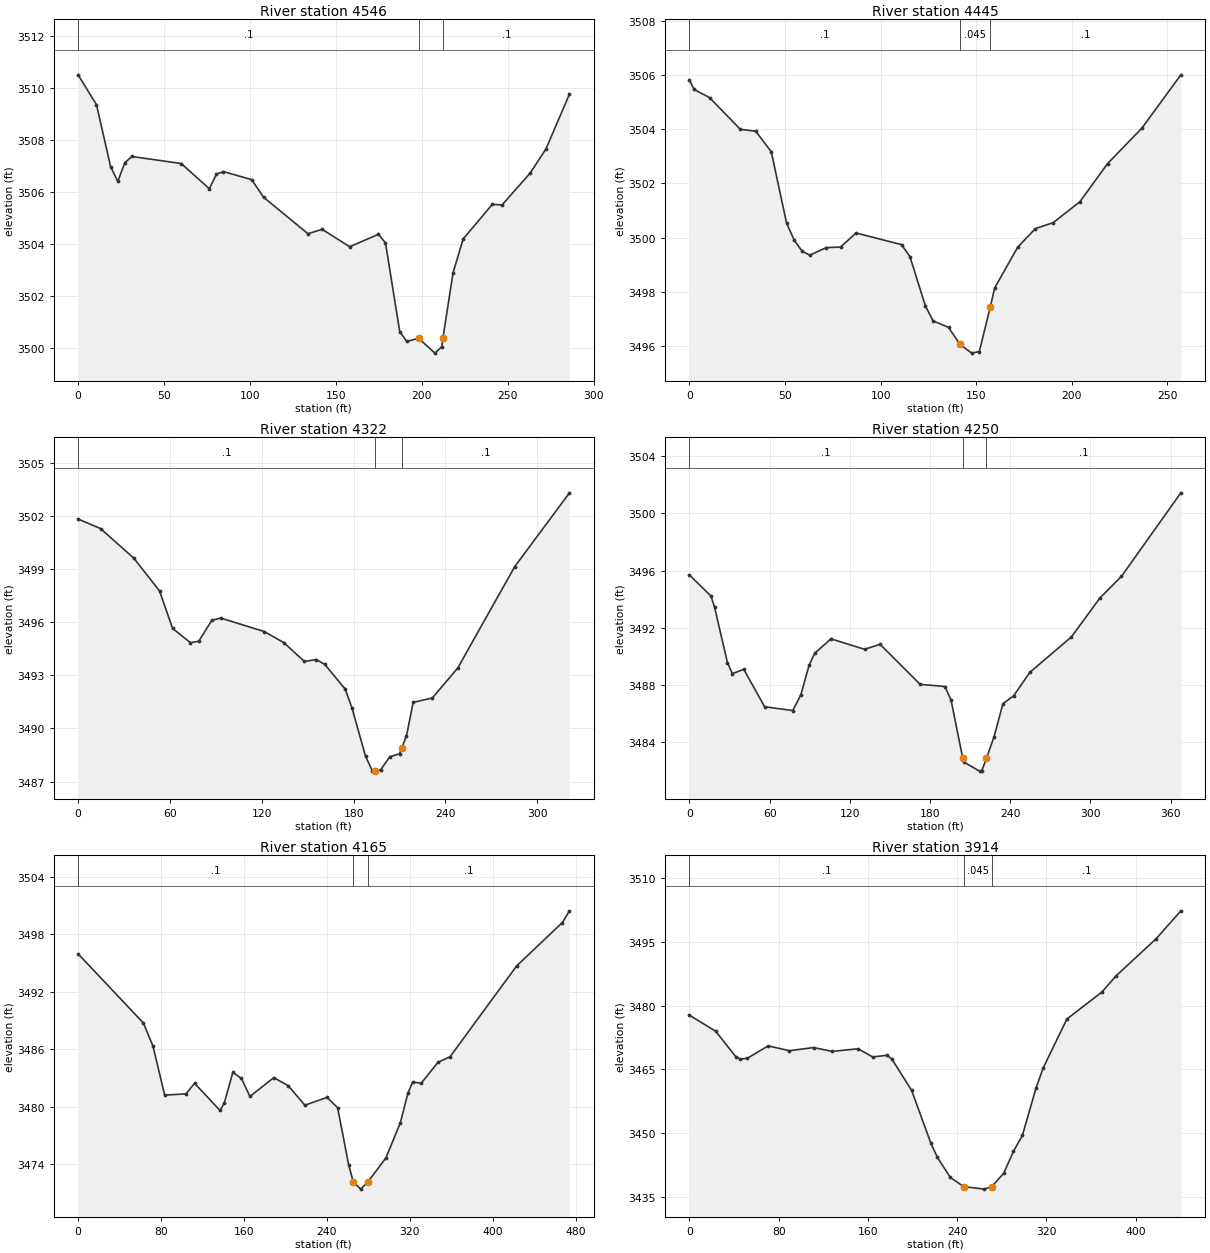
Type RM Length L Ch R = 1 ,4546    ,100.7,100.7,100.7
XS GIS Cut Line= 3
2203646.97976507525154.7035571772203596.81253787525374.856424909
2203640.95795634525415.845775263
#Sta/Elev= 30
       0  3510.5    10.7 3509.35    18.9 3506.97    23.1  3506.4    27.2 3507.12
    31.3 3507.36      60 3507.09    76.4 3506.12    80.5 3506.68    84.6 3506.78
     101 3506.47     108 3505.79   133.8 3504.39     142 3504.56   158.1 3503.89
   174.8 3504.37   178.9 3504.04   187.2 3500.63   191.3 3500.25   198.2 3500.37
   207.7  3499.8   211.6 3500.04   212.43500.399   218.2 3502.88   224.1 3504.19
   241.1 3505.52   246.8  3505.5   263.1 3506.72   272.3 3507.65     286 3509.76
#Mann= 3 ,-1,0
       0      .1       0   198.2    .045       0   212.4      .1       0
Bank Sta=198.2,212.4
XS Rating Curve= 0 ,0
Exp/Cntr=0.3,0.1

Type RM Length L Ch R = 1 ,4445    ,123.4,123.4,123.4
XS GIS Cut Line= 3
2203486.84958976525190.7488563322203508.12256246 525361.92207849
2203551.16322815525434.645961893
#Sta/Elev= 30
       0 3505.81     2.4 3505.46    10.5 3505.16    26.6 3503.99    34.7 3503.92
    42.8 3503.16    50.8 3500.53    54.8  3499.9    58.9  3499.5    62.9 3499.35
    71.5 3499.63      79 3499.65    87.1 3500.17   110.9 3499.74   115.3  3499.3
   123.4 3497.48   127.4 3496.93   135.5 3496.69   141.43496.069   147.6 3495.74
   151.6  3495.8   157.33497.433   159.6 3498.14   171.7 3499.65   180.9 3500.33
   190.2 3500.55   204.2 3501.32   218.7 3502.73   236.7 3504.04     257    3506
#Mann= 3 ,-1,0
       0      .1       0   141.4    .045       0   157.3      .1       0
Bank Sta=141.4,157.3
XS Rating Curve= 0 ,0
Exp/Cntr(USF)=0,0
Exp/Cntr=0.3,0.1

Type RM Length L Ch R = 1 ,4322    ,72.5,72.5,72.5
XS GIS Cut Line= 4
2203420.99100804525215.3858444452203374.68480942525338.446682373
2203416.39846032 525424.941625742203506.83656734525448.576342746
#Sta/Elev= 30
       0 3501.82    14.7 3501.28    36.4 3499.61    53.2 3497.76    61.7 3495.65
    73.4 3494.84    78.8 3494.92    87.4 3496.11    93.2 3496.23   121.6 3495.47
   134.5 3494.84   147.8 3493.78   155.6 3493.89   161.2 3493.61   174.5 3492.22
   178.9 3491.16   187.8 3488.42   192.2 3487.61   194.13487.601   194.6 3487.59
   197.6 3487.66   203.6  3488.4     210 3488.57   211.3 3488.87   214.5 3489.58
   218.9 3491.47   231.4 3491.72     248 3493.41   285.2 3499.13     321  3503.3
#Mann= 3 ,-1,0
       0      .1       0   194.1    .045       0   211.3      .1       0
Bank Sta=194.1,211.3
XS Rating Curve= 0 ,0
Exp/Cntr(USF)=0,0
Exp/Cntr=0.3,0.1

Type RM Length L Ch R = 1 ,4250    ,85,85,85
XS GIS Cut Line= 5
2203281.89870271525229.3723663162203312.96278953525385.415221027
2203348.36140009525447.5433946632203406.87747061525454.767600899
2203484.17647734525465.603910254
#Sta/Elev= 30
       0  3495.7    16.1 3494.23    18.8 3493.44    28.4 3489.58    32.1 3488.81
    40.6 3489.11    56.2  3486.5    77.3 3486.23    83.4 3487.35    89.5  3489.4
    93.6 3490.22   105.8 3491.24     131 3490.51   142.6 3490.86   172.6 3488.06
   191.1 3487.91   195.7 3486.96  204.41 3482.91   205.3 3482.63     217    3482
   218.7 3482.03   222.2  3482.9   227.9 3484.41   234.5 3486.71   242.5 3487.26
   254.6  3488.9   285.7 3491.37   307.1  3494.1   323.2 3495.61   367.6 3501.44
#Mann= 3 ,-1,0
       0      .1       0  204.41    .045       0   222.2      .1       0
Bank Sta=204.41,222.2
XS Rating Curve= 0 ,0
Exp/Cntr(USF)=0,0
Exp/Cntr=0.3,0.1

Type RM Length L Ch R = 1 ,4165    ,251,251,251
XS GIS Cut Line= 5
2203182.78375062525243.8628574252203234.10955976525463.328976284
  2203290.465068 525492.867365112203321.74837157525476.182380406
2203471.06090429525481.285464606
#Sta/Elev= 30
       0 3495.93      63 3488.71    72.2  3486.3    83.5 3481.19     104 3481.32
   112.3 3482.42   136.9 3479.59     141 3480.38   149.2 3483.56   157.5 3482.93
   165.7 3481.05   188.7 3483.01   202.6 3482.18   218.7 3480.14   240.1 3480.95
   250.3 3479.87   260.9 3473.93   265.43472.121   272.5 3471.38  279.44 3472.13
   296.9 3474.65   310.7 3478.28   318.2 3481.44   322.7 3482.56   330.9 3482.43
   347.1 3484.62   358.7 3485.19     423 3494.68     467 3499.19   473.9 3500.42
#Mann= 3 ,-1,0
       0      .1       0   265.4    .045       0  279.44      .1       0
Bank Sta=265.4,279.44
XS Rating Curve= 0 ,0
Exp/Cntr=0.3,0.1

Type RM Length L Ch R = 1 ,3914    ,275.8,275.8,275.8
XS GIS Cut Line= 4
2203007.77567171525448.0396685832203100.58125582525546.605599284
2203185.06633927525743.7374606872203253.55045996525803.261042215
#Sta/Elev= 30
       0 3477.74    23.5 3473.98    41.4 3468.01    45.5 3467.41      52 3467.62
    70.6 3470.52    89.5 3469.39   111.4 3470.12   127.9 3469.22   151.2 3469.84
   164.3 3467.91   177.3 3468.31   181.7 3467.32   199.1 3460.08   216.5 3447.56
   222.3 3444.24   233.9 3439.51   245.93437.352   264.4 3436.76   271.1 3437.35
   281.8 3440.52   290.5 3445.67   298.5 3449.41   310.7 3460.53   317.1 3465.28
   338.4 3476.84   369.9 3483.23   382.5 3487.02   418.3 3495.74440.5911 3502.35
#Mann= 3 ,-1,0
       0      .1       0   245.9    .045       0   271.1      .1       0
Bank Sta=245.9,271.1
XS Rating Curve= 0 ,0
Exp/Cntr(USF)=0,0
Exp/Cntr=0.3,0.1

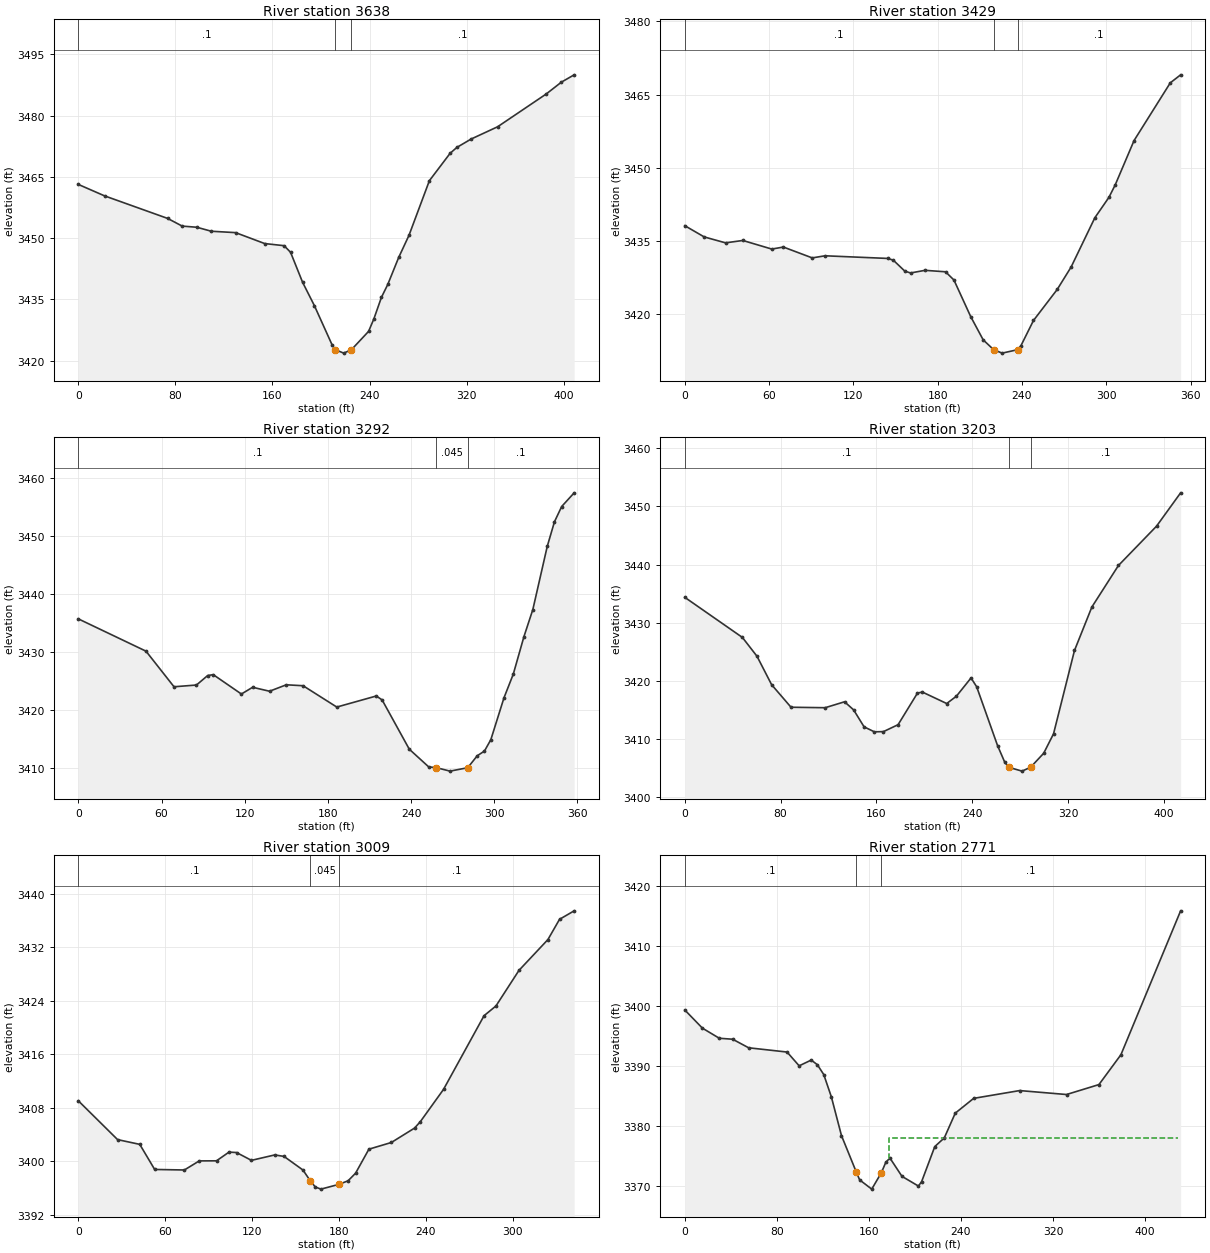
Type RM Length L Ch R = 1 ,3638    ,209,209,209
XS GIS Cut Line= 3
2202913.21926067525627.5999614892202915.12746342525798.204953766
2203085.37460202525964.562021777
#Sta/Elev= 30
       0 3463.15    21.6 3460.35    73.6 3454.82    85.6 3452.94    97.6 3452.66
   109.6 3451.68   129.6 3451.34   153.6 3448.66   169.6 3448.14   174.9 3446.52
   184.8 3439.18   194.5 3433.47   209.2 3423.79   211.83422.655   218.7 3421.82
     2253422.643   239.2 3427.15   243.6 3430.25   249.8  3435.5     255 3438.64
     264 3445.26   272.5 3450.69   289.3 3464.07   306.4 3470.78   311.9 3472.21
   323.7 3474.27   345.5 3477.27   385.6 3485.31   398.1 3488.21   408.6    3490
#Mann= 3 ,-1,0
       0      .1       0   211.8    .045       0     225      .1       0
Bank Sta=211.8,225
XS Rating Curve= 0 ,0
Exp/Cntr=0.3,0.1

Type RM Length L Ch R = 1 ,3429    ,137.5,137.5,137.5
XS GIS Cut Line= 3
2202739.59953559525809.0213888142202780.56200029525976.711478709
2202941.85170508526057.356331101
#Sta/Elev= 30
       0 3438.13    13.8 3435.83      29 3434.61    41.3  3435.1    61.9 3433.34
    70.2 3433.75    90.7 3431.53    99.9 3431.96   144.3 3431.42   148.4 3431.07
   156.6 3428.82   160.7 3428.44     171 3428.98   185.6 3428.68   191.6 3426.99
   203.5 3419.51   212.4 3414.73   219.83412.727   225.9 3412.01     237 3412.72
   239.3 3413.54   248.2  3418.7   265.1 3425.06     275 3429.66   291.9 3439.76
   301.9 3443.93   306.4  3446.5   319.8 3455.58   345.6 3467.41 352.948 3469.05
#Mann= 3 ,-1,0
       0      .1       0   219.8    .045       0     237      .1       0
Bank Sta=219.8,237
XS Rating Curve= 0 ,0
Exp/Cntr(USF)=0,0
Exp/Cntr=0.3,0.1

Type RM Length L Ch R = 1 ,3292    ,89.1,89.1,89.1
XS GIS Cut Line= 4
2202682.83045008525845.0035955012202716.41611623526059.951858887
2202767.91413767526132.7208022212202807.09741485526165.186946169
#Sta/Elev= 30
       0 3435.69    48.8 3430.12      69 3423.98    85.2 3424.28    93.3 3425.92
    97.3 3426.07   117.6 3422.73   125.7 3423.89   137.9 3423.21     150 3424.32
   162.1 3424.16   186.4 3420.48   214.9 3422.39   219.1 3421.71   238.7 3413.21
   252.7 3410.16   258.3 3410.02   268.1 3409.43  280.85 3410.02   287.7 3412.08
   292.9 3412.89   297.5 3414.85     307 3422.08   313.7 3426.16   321.4 3432.64
   327.8  3437.3   338.2  3448.2   343.4 3452.44   348.6 3455.07   357.6 3457.43
#Mann= 3 ,-1,0
       0      .1       0   258.3    .045       0  280.85      .1       0
Bank Sta=258.3,280.85
XS Rating Curve= 0 ,0
Exp/Cntr(USF)=0,0
Exp/Cntr=0.3,0.1

Type RM Length L Ch R = 1 ,3203    ,193.4,193.4,193.4
XS GIS Cut Line= 4
 2202604.1765838525869.7918764682202645.77908702526105.326048533
2202697.62220641526191.7312475252202768.02644263526214.772633922
#Sta/Elev= 30
       0 3434.37    48.1 3427.47    60.3 3424.23    72.5 3419.34    88.7 3415.46
   117.2 3415.38   133.4  3416.4     141    3415   149.7 3412.09   158.3 3411.23
   165.9 3411.27   178.1 3412.46   194.3  3417.9   198.4 3418.07   218.7  3416.1
   226.8 3417.36     239  3420.5   243.7 3418.99   261.2 3408.84     267 3406.08
   270.43405.136   281.6 3404.47   288.83405.145   299.7 3407.55   307.9 3410.89
   325.4 3425.23   339.9  3432.7   362.1 3439.85   393.9 3446.61414.0237 3452.35
#Mann= 3 ,-1,0
       0      .1       0   270.4    .045       0   288.8      .1       0
Bank Sta=270.4,288.8
XS Rating Curve= 0 ,0
Exp/Cntr(USF)=0,0
Exp/Cntr=0.3,0.1

Type RM Length L Ch R = 1 ,3009    ,238.1,238.1,238.1
XS GIS Cut Line= 3
2202399.15241447 526172.105234722202564.71034878526305.485183035
2202694.31047673526311.577916217
#Sta/Elev= 30
       0 3409.07    27.1 3403.27    42.4 3402.56    52.7 3398.81    73.2 3398.73
    83.5 3400.09    95.4  3400.1     104  3401.4   109.2 3401.34   119.5 3400.17
   135.6 3400.98     142 3400.76   155.1 3398.72   160.13397.121   163.6 3396.19
   167.5 3395.87   179.83396.579   186.2 3397.11   191.4 3398.25   200.6 3401.84
   216.1 3402.84   232.1 3404.99   236.1 3405.95   252.1 3410.77   280.1 3421.79
   288.3 3423.24   304.2 3428.56   324.2 3433.17   332.2 3436.19   342.3 3437.46
#Mann= 3 ,-1,0
       0      .1       0   160.1    .045       0   179.8      .1       0
#XS Ineff= 2 , 0
          104.05    3400
Permanent Ineff=
       F       F
Bank Sta=160.1,179.8
XS Rating Curve= 0 ,0
Exp/Cntr=0.3,0.1

Type RM Length L Ch R = 1 ,2771    ,307.8,307.8,307.8
XS GIS Cut Line= 3
2202232.54658935526326.4999679082202409.12393849 526477.10002982
2202608.01681486 526475.90834643
#Sta/Elev= 30
       0 3399.31    15.3 3396.28      30 3394.59    41.6 3394.43    55.5    3393
    88.9 3392.29    99.4 3389.99   109.9 3390.95   115.2 3390.18   120.8 3388.53
   127.4 3384.81   136.2 3378.34   149.2  3372.2     152 3370.95   162.5 3369.41
  170.84 3372.14   174.7 3373.88   178.3  3374.6   188.8 3371.54   203.1 3369.92
   205.9 3370.68   217.3 3376.51   225.6 3377.97   235.1 3382.09   251.1 3384.56
   291.1 3385.86   331.8  3385.2     360 3386.86   379.1 3391.84     431 3415.86
#Mann= 3 ,-1,0
       0      .1       0   149.2    .045       0  170.84      .1       0
#XS Ineff= 1 ,-1
  177.55 428.408    3378
Permanent Ineff=
       F
Bank Sta=149.2,170.84
XS Rating Curve= 0 ,0
Exp/Cntr(USF)=0,0
Exp/Cntr=0.3,0.1

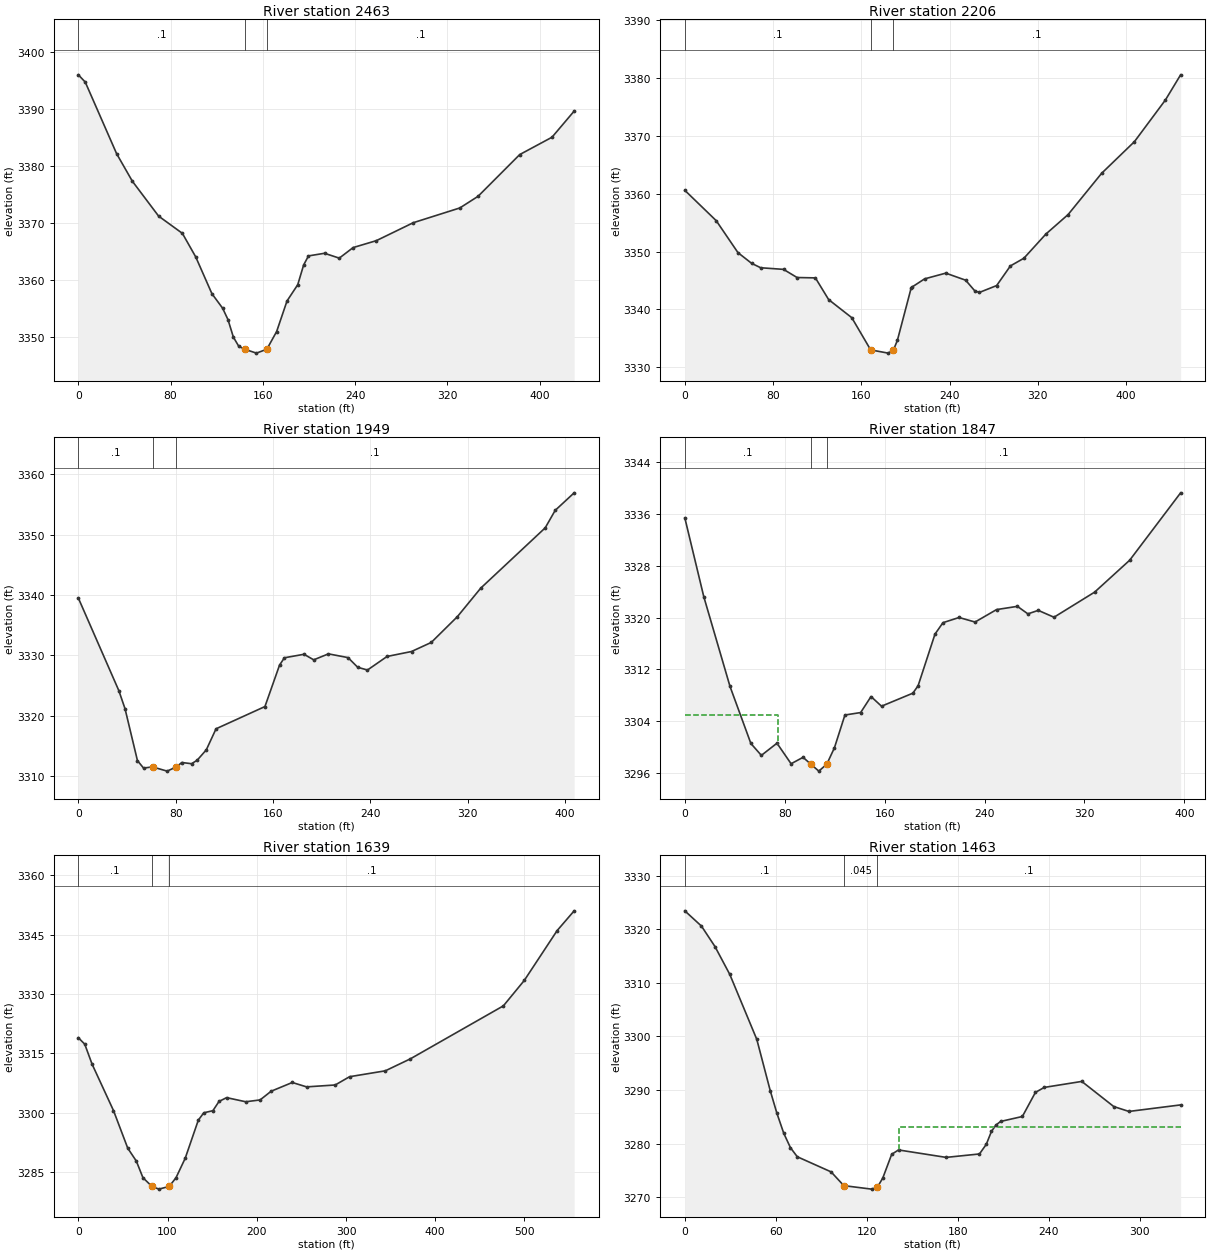
Type RM Length L Ch R = 1 ,2463    ,257.3,257.3,257.3
XS GIS Cut Line= 4
2202147.29445558526591.8556393152202184.42814492526661.464750661
2202304.86697522526732.8482102282202515.29216632526718.740979651
#Sta/Elev= 30
       0 3395.92       6 3394.65    33.2  3382.1    46.8 3377.29    69.6 3371.17
    90.2 3368.15   101.8 3364.01   115.8 3357.58   125.1 3355.03   129.7 3353.05
   134.4 3349.97     139 3348.39   144.2 3347.85   154.4 3347.17   163.43347.854
   171.9 3350.95   180.9 3356.31   190.2 3359.16   195.3 3362.61   199.5  3364.2
   213.4 3364.66   226.2 3363.81   238.2 3365.66   258.3 3366.87   290.4 3370.02
   330.7  3372.6   346.5 3374.64   382.6 3381.95   410.6 3384.99   429.8 3389.57
#Mann= 3 ,-1,0
       0      .1       0   144.2    .045       0   163.4      .1       0
Bank Sta=144.2,163.4
XS Rating Curve= 0 ,0
Exp/Cntr=0.3,0.1

Type RM Length L Ch R = 1 ,2206    ,257,257,257
XS GIS Cut Line= 3
2202021.49507866526901.2449842692202291.16625442526970.079522953
2202462.00812861526958.886448054
#Sta/Elev= 30
       0 3360.58    28.5 3355.33    48.2 3349.81    60.6 3347.96    68.8  3347.2
    89.5 3346.92   101.8 3345.51   118.4 3345.45   130.4  3341.7   151.4 3338.57
   168.53333.008   184.4 3332.45   189.23333.016   192.7 3334.64   205.1 3343.62
   206.1 3343.88   217.4 3345.28   236.6 3346.27   254.6 3345.05   262.8 3343.23
     267 3342.93   282.7 3344.12   295.2 3347.52   307.4 3348.84   327.4 3353.03
   347.5 3356.39   377.9 3363.52   407.6 3368.98   435.7 3376.18   449.5 3380.53
#Mann= 3 ,-1,0
       0      .1       0   168.5    .045       0   189.2      .1       0
Bank Sta=168.5,189.2
XS Rating Curve= 0 ,0
Exp/Cntr=0.3,0.1

Type RM Length L Ch R = 1 ,1949    ,101.8,101.8,101.8
XS GIS Cut Line= 4
2201974.11276863527101.0837850032202013.13383172527132.144214397
2202244.81293653527153.6850797042202367.48591889527129.463867104
#Sta/Elev= 30
       0 3339.51    33.3 3324.15    38.4 3321.14    48.6 3312.54    53.6 3311.31
      61  3311.5      73  3310.8   80.45 3311.49    85.1 3312.23    93.1 3312.03
    97.7 3312.61   105.2 3314.33   113.2 3317.82   153.4 3321.51   165.4 3328.38
   169.4  3329.6   185.5 3330.18   193.5 3329.26   205.6 3330.25   221.7 3329.63
   229.7 3328.02   237.7 3327.57   253.8 3329.82   273.9 3330.64   290.1 3332.14
   311.6 3336.42   330.8 3341.15   383.8 3351.15     392 3354.05   407.6 3356.96
#Mann= 3 ,-1,0
       0      .1       0      61    .045       0   80.45      .1       0
Bank Sta=61,80.45
XS Rating Curve= 0 ,0
Exp/Cntr(USF)=0,0
Exp/Cntr=0.3,0.1

Type RM Length L Ch R = 1 ,1847    ,208.9,208.9,208.9
XS GIS Cut Line= 3
2201909.60879903527201.408487924 2202201.6553267527291.104119589
2202292.88160054527297.838945174
#Sta/Elev= 30
       0  3335.4    15.2 3323.22    36.2 3309.37    52.9 3300.57    61.3 3298.73
    73.8 3300.61    85.1 3297.44    94.7 3298.43   101.1 3297.34   107.3  3296.3
   113.73297.378   119.8  3299.9   128.2 3304.96   140.8 3305.34   149.1 3307.81
   157.5 3306.32   182.6 3308.33   186.8 3309.48   200.3 3317.44   206.7 3319.21
   219.6 3320.01   232.4 3319.31   249.6 3321.23   266.3 3321.73   274.7 3320.57
     283 3321.11   295.6 3320.05   328.1 3323.92   356.2 3328.85396.9847 3339.25
#Mann= 3 ,-1,0
       0      .1       0   101.1    .045       0   113.7      .1       0
#XS Ineff= 2 , 0
        74.92007    3305
Permanent Ineff=
       F       F
Bank Sta=101.1,113.7
XS Rating Curve= 0 ,0
Exp/Cntr(USF)=0,0
Exp/Cntr=0.3,0.1

Type RM Length L Ch R = 1 ,1639    ,176.2,176.2,176.2
XS GIS Cut Line= 4
2201833.09485222527377.3280346912201882.77837781 527388.24988483
2201976.60373971527464.8887465232202359.26383659527436.248477557
#Sta/Elev= 30
       0 3318.93     7.2 3317.29    15.4 3312.25    39.4 3300.52    55.4    3291
      65 3287.75    72.4 3283.55    82.53281.344    90.3 3280.66   101.93281.353
   109.5 3283.55   119.8 3288.47   134.5 3298.11   140.6 3299.95   150.8 3300.48
   157.7 3302.83   166.2 3303.78   187.6 3302.74   203.7  3303.2   216.1  3305.4
   239.8 3307.61   255.8  3306.5   287.9 3306.98     304 3309.07   344.1 3310.56
   372.1 3313.58   476.4 3326.98   499.8  3333.4   536.6 3345.99   555.7 3350.99
#Mann= 3 ,-1,0
       0      .1       0    82.5    .045       0   101.9      .1       0
Bank Sta=82.5,101.9
XS Rating Curve= 0 ,0
Exp/Cntr=0.3,0.1

Type RM Length L Ch R = 1 ,1463    ,155.6,155.6,155.6
XS GIS Cut Line= 3
2201732.13922215527418.5470069162201824.52143836527607.302889571
2201919.99024803527674.825095431
#Sta/Elev= 30
       0 3323.44      11 3320.59    19.9 3316.78    29.7 3311.57    47.5 3299.46
    56.4 3289.86    60.8 3285.65    65.3 3281.94    69.7 3279.26    74.2 3277.57
    96.5 3274.75   104.93272.182   123.2 3271.53     1273271.875   130.6 3273.59
   136.5 3278.03     141 3278.84   172.4 3277.45   194.4 3278.09   198.9 3279.89
   202.3  3282.3   205.3 3283.49   208.3 3284.15   222.7 3285.08   231.3 3289.57
   237.1  3290.5   261.9 3291.62     283 3286.93     293 3286.02   327.1 3287.24
#Mann= 3 ,-1,0
       0      .1       0   104.9    .045       0     127      .1       0
#XS Ineff= 2 , 0
                          141.52         3283.08
Permanent Ineff=
       F       F
Bank Sta=104.9,127
XS Rating Curve= 0 ,0
Exp/Cntr(USF)=0,0
Exp/Cntr=0.3,0.1

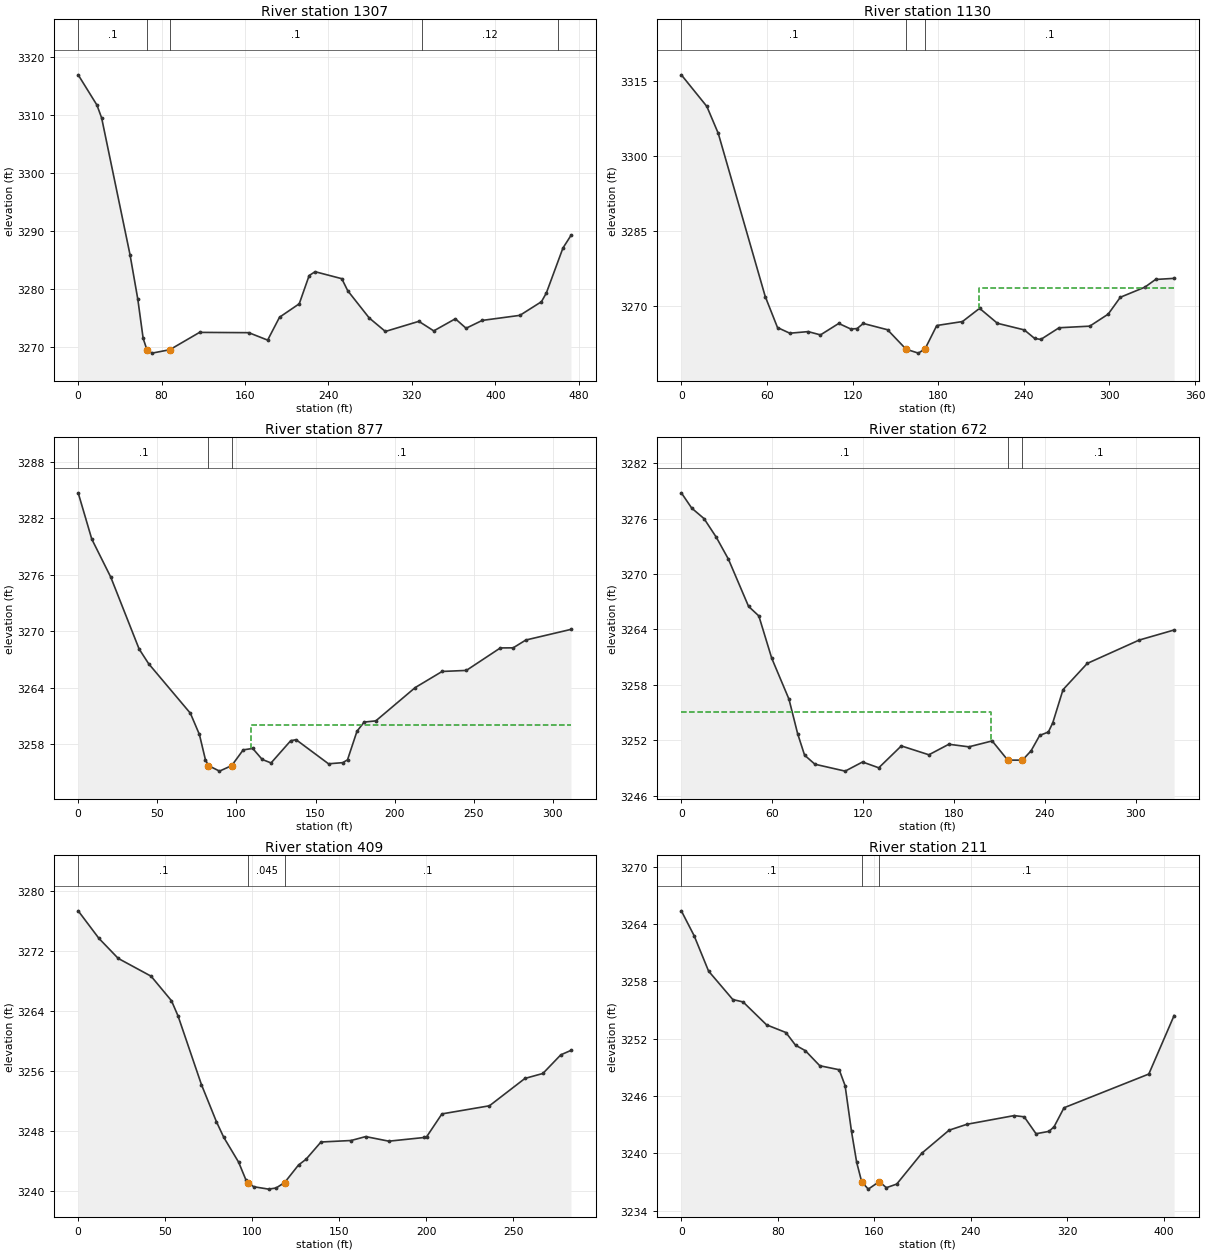
Type RM Length L Ch R = 1 ,1307    ,177.3,177.3,177.3
XS GIS Cut Line= 2
2201596.78522066527516.8684255352201895.45410994 527883.14626518
#Sta/Elev= 30
       0 3316.88      18 3311.67    22.5 3309.46    49.7 3285.94    57.2 3278.25
    62.3 3271.53    65.9 3269.59    70.9 3268.99    87.9 3269.58   116.4 3272.56
   163.6 3272.51   181.7 3271.23   193.1 3275.17     212 3277.48   221.5 3282.34
   227.2    3283   252.8  3281.8   258.5 3279.73   279.1 3275.04   294.6 3272.72
   326.7 3274.46     341 3272.82   361.7  3274.9     372 3273.27   387.5 3274.62
   423.6 3275.49   444.3 3277.84     449 3279.35   464.9 3287.08   472.6 3289.25
#Mann= 5 ,-1,0
       0      .1       0    65.9    .045       0    87.9      .1       0
     330     .12       0     460      .1       0
Bank Sta=65.9,87.9
XS Rating Curve= 0 ,0
Exp/Cntr(USF)=0,0
Exp/Cntr=0.3,0.1

Type RM Length L Ch R = 1 ,1130    ,251.9,251.9,251.9
XS GIS Cut Line= 3
2201504.14982762527559.2484203432201504.51524192527604.510461009
2201612.88442765527884.341224854
#Sta/Elev= 30
       0 3316.26    17.9 3309.94    25.9 3304.55    58.8 3271.96    67.4 3265.76
      76 3264.63    88.9 3264.95    97.5 3264.29   110.3 3266.58   118.9 3265.45
   123.2 3265.57   127.5 3266.58   144.5 3265.32   157.5 3261.43   166.1 3260.65
   170.83261.507     179 3266.17     197 3266.96     209  3269.6   221.5 3266.61
   240.3 3265.29   247.6 3263.58   251.9 3263.39   264.7 3265.72   286.2 3266.04
   299.1 3268.44   307.6 3271.81   324.8 3273.83   332.3 3275.37   345.3 3275.59
#Mann= 3 ,-1,0
       0      .1       0   157.5    .045       0   170.8      .1       0
#XS Ineff= 2 , 0
                          208.78         3273.74
Permanent Ineff=
       F       F
Bank Sta=157.5,170.8
XS Rating Curve= 0 ,0
Exp/Cntr=0.3,0.1

Type RM Length L Ch R = 1 ,877     ,205,205,205
XS GIS Cut Line= 2
2201253.74378317 527719.436157512201485.38096619527927.603493794
#Sta/Elev= 30
       0  3284.7     8.6 3279.78    20.6 3275.74    38.5 3268.11    44.5 3266.55
    70.9 3261.28    76.6 3259.03    80.4 3256.35    82.3 3255.72    89.3 3255.13
      973255.714   104.3 3257.39   110.3 3257.54   116.3 3256.37   121.9    3256
   134.3 3258.36   137.7 3258.47   158.2 3255.91   167.2 3256.03   170.2 3256.33
   176.2 3259.37   180.7 3260.34   188.1 3260.47     213 3264.01     230 3265.72
   245.3 3265.83   266.8 3268.22   274.9 3268.23   282.9 3269.06311.4312 3270.19
#Mann= 3 ,-1,0
       0      .1       0    82.3    .045       0      97      .1       0
#XS Ineff= 2 , 0
       0                 109.185       0    3260
Permanent Ineff=
       F       F
Bank Sta=82.3,97
XS Rating Curve= 0 ,0
Exp/Cntr(USF)=0,0
Exp/Cntr=0.3,0.1

Type RM Length L Ch R = 1 ,672     ,262.8,262.8,262.8
XS GIS Cut Line= 3
2201043.47456247527786.283949666 2201048.2731616527827.322386944
2201274.58435952 527999.15578534
#Sta/Elev= 30
       0 3278.78     6.9 3277.12      15 3275.99    23.1 3273.97    31.1  3271.6
    44.4 3266.49    51.2 3265.45    59.7 3260.88    71.1 3256.44    76.8 3252.72
    81.4 3250.38   88.233249.398   108.2 3248.65   119.7 3249.64   130.4 3249.01
   145.3 3251.38   163.5 3250.42   176.7 3251.56   189.9 3251.28   205.3 3251.92
   215.63249.842   225.3 3249.84     231 3250.85   236.7 3252.52   242.4 3252.88
   245.3 3253.87   252.1 3257.47   268.1 3260.31   302.4 3262.84 325.472 3263.93
#Mann= 3 ,-1,0
       0      .1       0   215.6    .045       0   225.3      .1       0
#XS Ineff= 2 , 0
        204.8096    3255
Permanent Ineff=
       F       F
Bank Sta=215.6,225.3
XS Rating Curve= 0 ,0
Exp/Cntr(USF)=0,0
Exp/Cntr=0.3,0.1

Type RM Length L Ch R = 1 ,409     ,198.7,198.7,198.7
XS GIS Cut Line= 3
2200923.83718392527839.247355798 2200975.9923989527973.036820294
2201104.49075463 528027.45965331
#Sta/Elev= 30
       0 3277.33    11.9 3273.67      23    3271    41.9 3268.63    53.6 3265.37
    57.4 3263.33    70.8 3254.22    79.4 3249.29    83.6 3247.21    92.2 3243.88
    96.5 3241.46    97.83241.156   100.8 3240.62   109.4  3240.3   113.7 3240.45
   118.63241.172   126.6 3243.51   130.9 3244.27   139.5 3246.57   156.8 3246.77
   165.2 3247.29   178.5 3246.68   198.8 3247.17   200.3  3247.3     209 3250.31
   236.3 3251.39   256.7 3255.03     267 3255.69   277.3 3258.17 283.144 3258.76
#Mann= 3 ,-1,0
       0      .1       0    97.8    .045       0   118.6      .1       0
Bank Sta=97.8,118.6
XS Rating Curve= 0 ,0
Exp/Cntr(USF)=0,0
Exp/Cntr=0.3,0.1

Type RM Length L Ch R = 1 ,211     ,117.6,117.6,117.6
XS GIS Cut Line= 4
 2200760.8315349527890.5805929742200767.85527713  528016.1299854
2200846.94225965528069.1733439562201028.47738277 528021.79256846
#Sta/Elev= 30
       0 3265.38    10.6 3262.78    22.6 3259.07    42.7 3256.09    51.2 3255.84
    70.7 3253.44    86.7 3252.64    94.7 3251.31   102.8 3250.74   114.8 3249.16
   130.9 3248.74   135.8 3247.07   141.1 3242.28   145.4 3239.04   149.53237.025
     155 3236.24   164.2 3237.03     170 3236.39   178.6 3236.77   199.4    3240
     222 3242.41   236.8 3243.03     276 3243.94   284.3 3243.81   294.1 3242.04
   304.9 3242.29   309.1 3242.78   317.3 3244.76   387.6 3248.29408.5901 3254.42
#Mann= 3 ,-1,0
       0      .1       0   149.5    .045       0   164.2      .1       0
Bank Sta=149.5,164.2
XS Rating Curve= 0 ,0
Exp/Cntr(USF)=0,0
Exp/Cntr=0.3,0.1

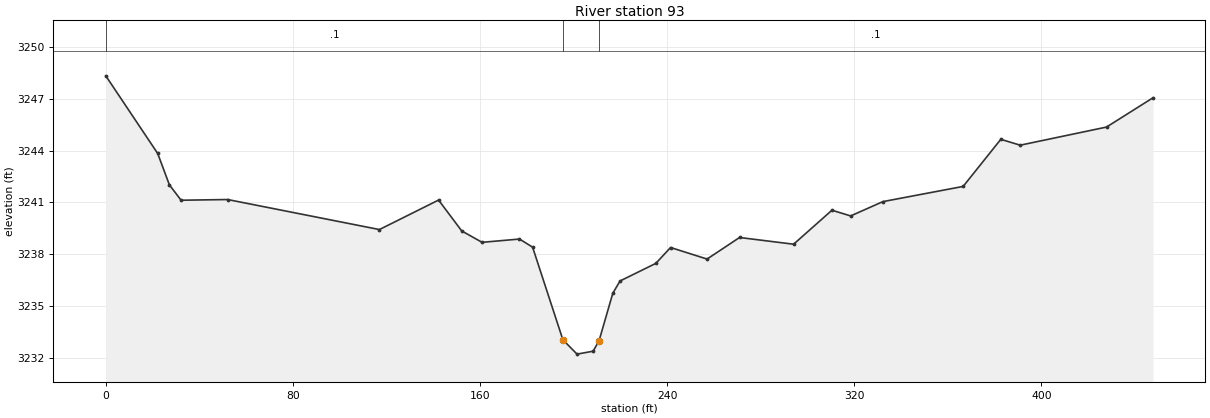
Type RM Length L Ch R = 1 ,93      ,,,
XS GIS Cut Line= 4
  2200613.744567528007.3834156032200698.31754428528120.910468036
 2200787.5873965528157.3590489912200969.45077494528052.685082845
#Sta/Elev= 30
       0 3248.34    22.2 3243.84    27.2 3242.02    32.2 3241.13    52.1 3241.17
     117 3239.43   142.3 3241.14   152.2 3239.35   160.9 3238.69   176.9 3238.88
   182.5 3238.41195.44633233.043   201.5 3232.21   208.4 3232.38210.94583232.996
   216.8 3235.74   219.9 3236.45   235.2 3237.47   241.5 3238.39   257.1 3237.72
     271 3238.97   294.1 3238.58   310.5 3240.55   318.5 3240.22   332.3 3241.05
   366.6 3241.93   382.7 3244.66     391 3244.32   427.9 3245.37   447.8 3247.07
#Mann= 3 ,-1,0
       0      .1       0195.4463    .045       0210.9458      .1       0
Bank Sta=195.4463,210.9458
XS Rating Curve= 0 ,0
Exp/Cntr(USF)=0,0
Exp/Cntr=0.3,0.1
LCMann Table=0

Chan Stop Cuts=-1
Use User Specified Reach Order=0
Composite Channel Slope=5